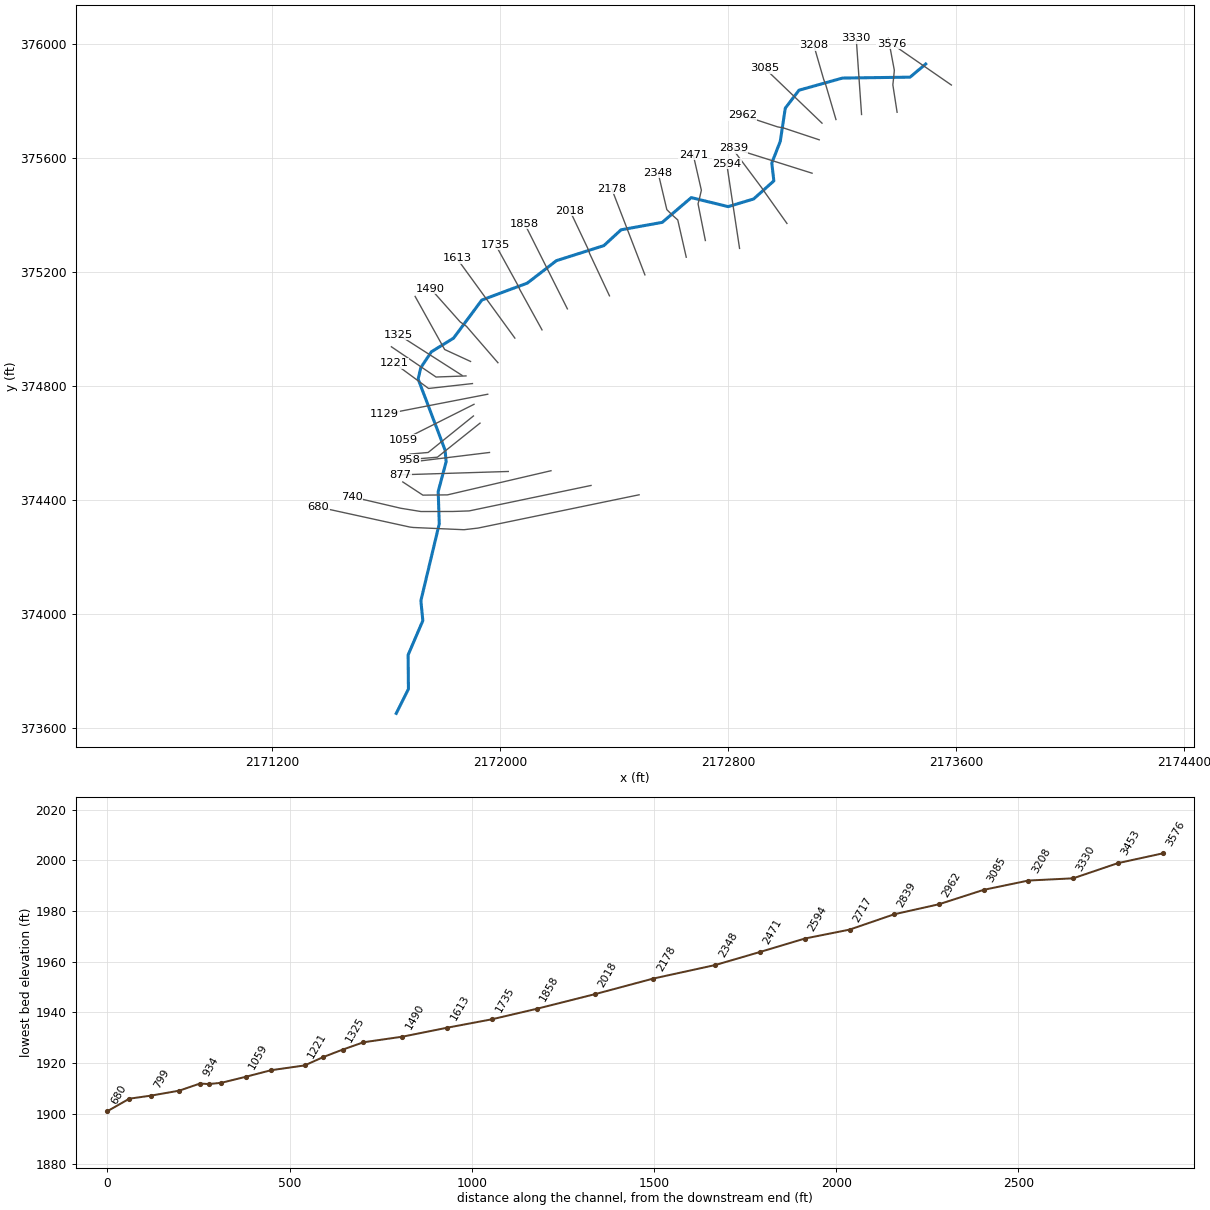
--- GRBRRVTR5.prj (project) ---

Proj Title=GRBRRVTR5
Current Plan=p01
Default Exp/Contr=0.3,0.1
English Units
Geom File=g02
Flow File=f01
Plan File=p01
BEGIN DESCRIPTION:
Stream Name- Greenbrier River Tributary 5
Flood Zone: Zone A
Greenbrier County, WV
County-Wide Study
WVDHSEM-2018-3, Flood Risk Project
HEC-RAS Version: 5.0.7
General Notes:
For the Hydrology regression was used.
END DESCRIPTION:
DSS Export Rating Curves= 0
DSS Export Rating Curve Sorted= 0
DSS Export Volume Flow Curves= 0
DXF OffsetX= 0
DXF OffsetY= 0
DXF ScaleX= 0
DXF ScaleY= 0

--- GRBRRVTR5.p01 (plan) ---

Plan Title=Floodplain
Program Version=5.07
Short Identifier=Floodplain
Geom File=g02
Flow File=f01
Subcritical Flow
K Sum by GR= 0
Std Step Tol= 0.01
Critical Tol= 0.01
Num of Std Step Trials= 20
Max Error Tol= 0.3
Flow Tol Ratio= 0.001
Split Flow NTrial= 30
Split Flow Tol= 0.02
Split Flow Ratio= 0.02
Log Output Level= 0
Friction Slope Method= 1
Unsteady Friction Slope Method= 2
Unsteady Bridges Friction Slope Method= 1
Parabolic Critical Depth
Global Vel Dist= 0 , 0 , 0
Global Log Level= 0
CheckData=True
Encroach Param=-1 ,0,0, 0
Mapping Interval=1HOUR
Computation Time Step Use Courant=        0
Computation Time Step Use Time Series=    0
Computation Time Step Count To Double=0
Computation Time Step Max Doubling=0
Computation Time Step Max Halving=0
Computation Time Step Residence Courant=0
Run HTab= 0
Run UNet= 0
Run Sediment= 0
Run PostProcess= 0
Run WQNet= 0
Run RASMapper=-1
UNET Theta= 0
UNET Theta Warmup= 0
UNET ZTol= 0
UNET ZSATol= 0
UNET MxIter= 0
UNET Max Iter WO Improvement= 0
UNET MaxInSteps= 0
UNET DtIC= 0
UNET DtMin= 0
UNET MaxCRTS= 0
UNET WFStab= 0
UNET SFStab= 0
UNET WFX= 1
UNET SFX= 1
UNET 1D Methodology=Finite Difference
UNET DSS MLevel= 1
UNET Pardiso=0
UNET DZMax Abort= 0
UNET Use Existing IB Tables= 0
UNET Froude Reduction=False
UNET Froude Limit= 0
UNET Froude Power= 0
UNET D1 Cores= 0
UNET D2 Coriolis=0
UNET D2 Cores= 0
UNET D2 Theta= 1
UNET D2 Theta Warmup= 1
UNET D2 Z Tol= 0.01
UNET D2 Volume Tol= 0.01
UNET D2 Max Iterations= 20
UNET D2 Equation= 0
UNET D2 RampUpFraction=0.1
UNET D2 TimeSlices= 1
UNET D2 BCVolumeCheck=0
UNET D1D2 MaxIter= 0
UNET D1D2 ZTol=0.01
UNET D1D2 QTol=0.1
UNET D1D2 MinQTol=1
Write IC File= 0
Write IC File at Fixed DateTime=0
Write IC File at Sim End=0
Echo Input=False
Echo Parameters=False
Echo Output=False
Write Detailed= 0
HDF Write Warmup=0
HDF Write Time Slices=0
HDF Flush=0
HDF Face Node Velocities=0
HDF Compression= 1
HDF Chunk Size= 1
HDF Spatial Parts= 1
HDF Use Max Rows=0
HDF Fixed Rows= 1
Calibration Method= 0
Calibration Iterations= 20
Calibration Max Change=0.05
Calibration Tolerance=0.2
Calibration Maximum=1.5
Calibration Minimum=0.5
Calibration Optimization Method= 1
WQ AD Non Conservative
WQ ULTIMATE=-1
WQ Max Comp Step=1HOUR
WQ Output Interval=15MIN
WQ Output Selected Increments= 0
WQ Output face flow=0
WQ Output face velocity=0
WQ Output face area=0
WQ Output face dispersion=0
WQ Output cell volume=0
WQ Output cell surface area=0
WQ Output cell continuity=0
WQ Output cumulative cell continuity=0
WQ Output face conc=0
WQ Output face dconc_dx=0
WQ Output face courant=0
WQ Output face peclet=0
WQ Output face adv mass=0
WQ Output face disp mass=0
WQ Output cell mass=0
WQ Output cell source sink temp=0
WQ Output nsm pathways=0
WQ Output nsm derived pathways=0
WQ Output MaxMinRange=-1
WQ Daily Max Min Mean=-1
WQ Daily Range=0
WQ Daily Time=0
WQ Create Restart=0
WQ Fixed Restart=0
WQ System Summary=0
WQ Write To DSS=0
WQ Use Fixed Temperature=0
Sorting and Armoring Iterations= 10
XS Update Threshold= 0.02
Bed Roughness Predictor= 0
Hydraulics Update Threshold= 0.02
Energy Slope Method= 1
Volume Change Method= 1
Sediment Retention Method= 0
XS Weighting Method= 0
Number of US Weighted Cross Sections= 1
Number of DS Weighted Cross Sections= 1
Upstream XS Weight=0
Main XS Weight=1
Downstream XS Weight=0
Number of DS XS's Weighted with US Boundary= 1
Upstream Boundary Weight= 1
Weight of XSs Associated with US Boundary= 0
Number of US XS's Weighted with DS Boundary= 1
Downstream Boundary Weight= 0.5
Weight of XSs Associated with DS Boundary= 0.5
Percentile Method= 0
Sediment Output Level= 3
Mass or Volume Output= 0
Output Increment Type= 1
Profile and TS Output Increment= 1
XS Output Flag= 0
XS Output Increment= 10
Write Gradation File= 0
Read Gradation Hotstart= 0
Write HDF5 File= 1
Write Binary Output= 1
Write DSS Sediment File= 0
SV Curve= 0
Specific Gage Flag= 0

--- GRBRRVTR5.f01 (steady flow) ---

Flow Title=Flow
Program Version=5.07
Number of Profiles= 6
Profile Names=f1p,f10p,f4p,f2p,f02p,f1pplus
River Rch & RM=Greenbrier River,A2              ,3576
     534     281     375     452     747     790
River Rch & RM=Greenbrier River,A2              ,1735
     597     316     420     505     833     883
Boundary for River Rch & Prof#=Greenbrier River,A2              , 1
Up Type= 0
Dn Type= 3
Dn Slope=0.033
Boundary for River Rch & Prof#=Greenbrier River,A2              , 2
Up Type= 0
Dn Type= 3
Dn Slope=0.033
Boundary for River Rch & Prof#=Greenbrier River,A2              , 3
Up Type= 0
Dn Type= 3
Dn Slope=0.033
Boundary for River Rch & Prof#=Greenbrier River,A2              , 4
Up Type= 0
Dn Type= 3
Dn Slope=0.033
Boundary for River Rch & Prof#=Greenbrier River,A2              , 5
Up Type= 0
Dn Type= 3
Dn Slope=0.033
Boundary for River Rch & Prof#=Greenbrier River,A2              , 6
Up Type= 0
Dn Type= 3
Dn Slope=0.033
DSS Import GetInterval= 0
DSS Import GetPeak= 0
DSS Import FillOption= 0

--- GRBRRVTR5.g02 (geometry) ---

Geom Title=Greenbrier River
Program Version=5.07

River Reach=Greenbrier River,A2
Reach XY= 30
2173494.26643939375929.4132299722173439.30887213375883.333269641
2173202.16662988375880.1511893872173049.69908705375837.557114482
2173001.65653223 375774.642214062172984.03058322375658.144087479
2172954.26555088375581.8935838042172961.52144189375519.432094559
 2172890.5783423375456.0175232292172801.30128989375429.108784392
2172671.71001364375460.7475006432172570.14919314375373.973395973
2172425.44475813375347.8356529772172365.10367148375292.305908397
2172198.69718014375239.5599508882172096.45296206375160.750725314
2171937.01922581375101.4431011382171837.68707539374967.565744221
2171760.08421221374919.8860495542171722.90449655374864.278549224
2171713.56429213 374824.175282972171807.88890664374575.414625645
2171811.74880706 374534.192267152171783.92012255374429.331584483
2171787.63796289374316.2924404742171723.15646455374046.582678065
2171729.97928555373976.5306528062171678.42361438373856.386536151
2171679.44920288373736.7968803052171636.75834338373651.253416225

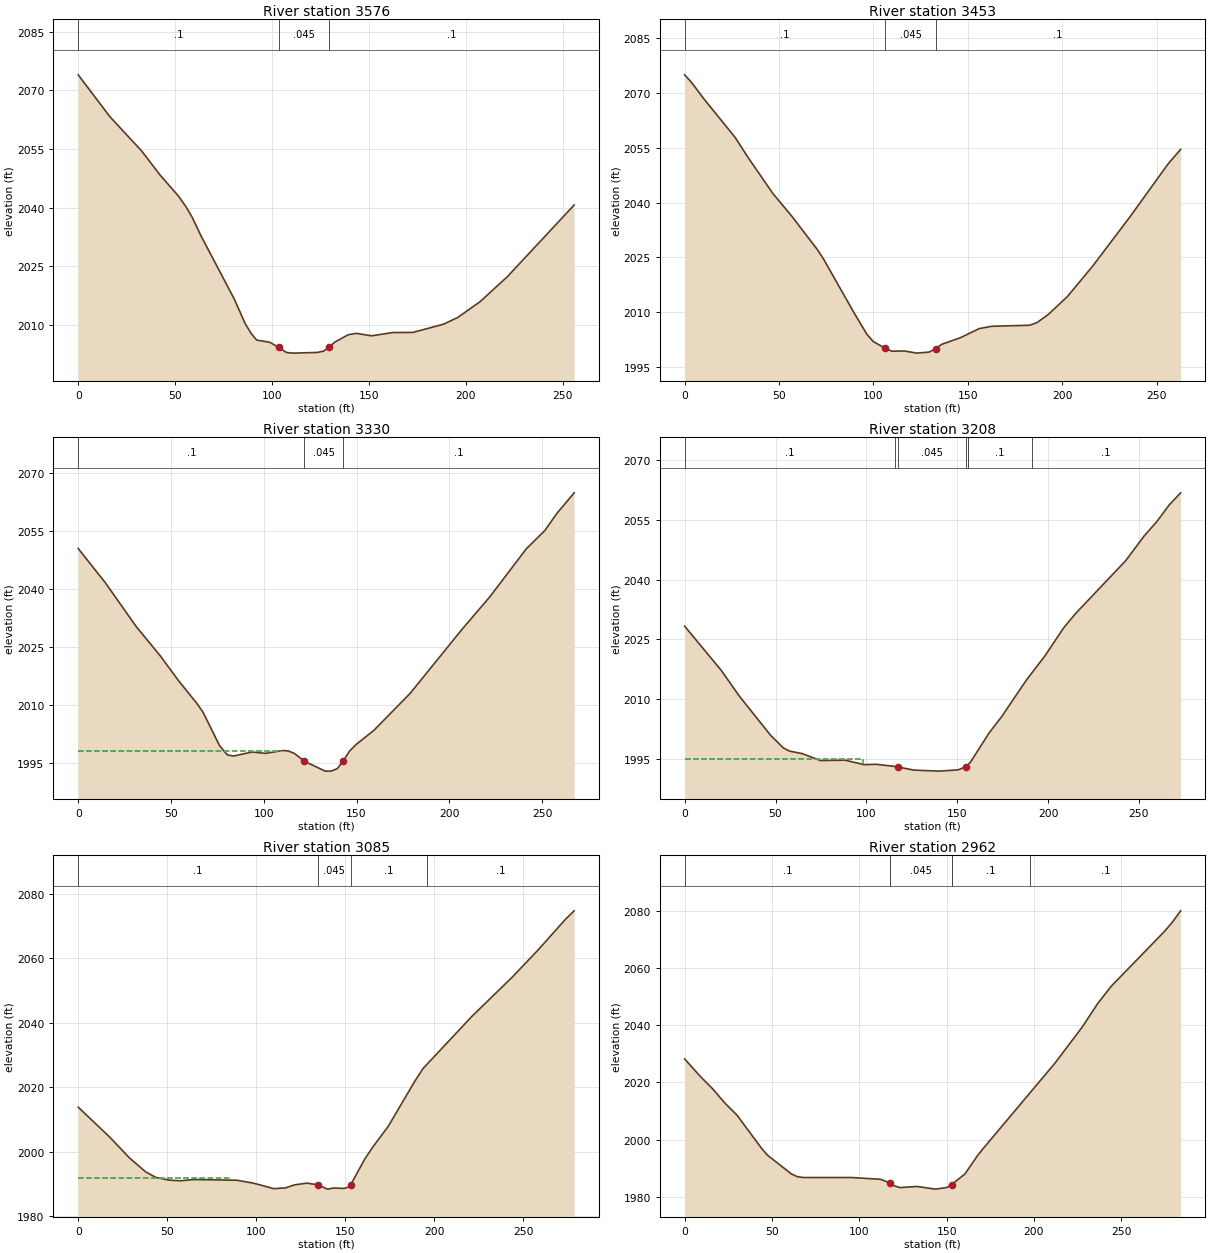
Type RM Length L Ch R = 1 ,3576    ,122.7,122.7,122.7
XS GIS Cut Line= 2
2173584.33414395375855.718834401 2173373.7858718376001.331658125
#Sta/Elev= 30
       0 2073.99    16.3  2063.3    32.8 2054.47    42.2 2048.37    51.7 2042.97
    55.7 2040.17    58.8 2037.54    63.6 2032.55    80.5 2016.63    86.3 2010.18
    89.4  2007.7    92.1 2006.07    98.8 2005.53   103.6 2004.18   107.5  2002.9
   110.6 2002.73   123.5 2002.91   126.7 2003.25   129.2 2004.18   132.4 2005.53
   139.4 2007.44   143.6 2007.79   151.4 2007.16   162.5 2008.01   172.8 2008.03
   188.5 2010.13   195.9 2011.85   207.3 2015.85   221.5 2022.29     256 2040.66
#Mann= 3 ,-1 , 0
       0      .1       0   103.6    .045       0   129.2      .1       0
Bank Sta=103.6,129.2
XS Rating Curve= 0 ,0
Exp/Cntr=0.3,0.1

Type RM Length L Ch R = 1 ,3453    ,122.7,122.7,122.7
XS GIS Cut Line= 5
2173393.89330492375760.1934958462173378.98141616375856.436234148
2173382.03501162 375883.803939082173384.18458684375907.555563043
2173363.15627252376019.547153302
#Sta/Elev= 30
       0 2074.87     3.6 2072.82    10.2  2068.3    26.8 2057.73    33.5 2052.37
    46.7 2042.49    56.7  2036.3      70 2027.36    73.3 2024.81    89.9 2009.74
    96.5 2004.06    99.8 2002.09   106.32000.191   109.7 1999.42   116.4 1999.47
     123 1998.89   129.5 1999.18   132.92000.087   136.1 2001.28     146 2003.09
     156 2005.58   162.7 2006.22   182.7  2006.5   186.7 2007.23   192.7 2009.49
   202.7 2014.32   216.1 2022.63     236  2036.2   256.1 2050.57   262.7 2054.52
#Mann= 3 ,-1 , 0
       0      .1       0   106.3    .045       0   132.9      .1       0
Bank Sta=106.3,132.9
XS Rating Curve= 0 ,0
Exp/Cntr=0.3,0.1

Type RM Length L Ch R = 1 ,3330    ,122.8,122.8,122.8
XS GIS Cut Line= 5
2173269.21255043375752.3791238152173269.21255043375752.379123815
2173259.86469314375885.7032465172173250.51683585 376019.02736922
2173250.51683585 376019.02736922
#Sta/Elev= 30
       0 2050.54    14.7 2041.63    31.1 2030.44    44.3 2022.71    54.1  2016.3
      64 2010.41    67.3 2008.13    76.2 1999.49    80.4  1997.1    83.7  1996.8
    93.6 1997.84     101  1997.5     110 1998.23   113.3 1998.12   116.6 1997.46
   121.91995.463   133.1  1992.9   136.4 1992.91   139.6 1993.53   142.71995.425
   146.2 1998.05   149.5 1999.68   159.4 2003.48   178.8 2012.98     207 2029.69
   221.9 2038.06   241.6 2050.52   251.5 2055.19     258 2059.63   267.3 2064.96
#Mann= 3 ,-1 , 0
       0      .1       0   121.9    .045       0   142.7      .1       0
#XS Ineff= 2 , 0
          109.78 1998.24
Permanent Ineff=
       F       F
Bank Sta=121.9,142.7
XS Rating Curve= 0 ,0
Exp/Cntr=0.3,0.1

Type RM Length L Ch R = 1 ,3208    ,122.8,122.8,122.8
XS GIS Cut Line= 5
2173179.41524978375734.6279171322173143.33394174375857.428238041
 2173139.7497585 375866.763123062173136.16557527375876.098008079
2173101.40875253375996.159849393
#Sta/Elev= 30
       0 2028.33    20.1 2017.28    30.1 2010.81    47.4 2000.94    54.3 1997.84
    57.7 1997.04    64.6 1996.42    74.8 1994.67    88.3 1994.76    98.7 1993.65
   105.6 1993.73   115.8 1993.19   117.4 1993.05   126.1 1992.28   140.1 1992.02
   150.6 1992.35   154.7 1993.11   156.2 1993.76   157.4 1994.32   167.6  2001.6
   174.5 2005.67   188.1 2014.83   198.4 2020.94   208.6  2027.9   215.4 2031.61
   242.8 2044.76     253 2050.97   259.9 2054.53   266.7  2058.7     273 2061.74
#Mann= 7 ,-1 , 0
       0      .1       0   115.8     .06       0   117.4    .045       0
   154.7     .06       0   156.2     .06       0   156.2      .1       0
     191      .1       0
#XS Ineff= 2 , 0
           97.911995.055
Permanent Ineff=
       F       F
Bank Sta=117.4,154.7
XS Rating Curve= 0 ,0
Exp/Cntr=0.3,0.1

Type RM Length L Ch R = 1 ,3085    ,122.7,122.7,122.7
XS GIS Cut Line= 5
2173130.46821661375721.9698598482173130.46821661375721.969859848
2173029.97498753375818.3653444952172929.48175844375914.760829143
2172929.48175844375914.760829143
#Sta/Elev= 30
       0 2013.79    17.7 2004.51    28.6 1998.14    37.9 1993.69    43.7 1991.98
    50.8 1991.17    57.3 1990.94    65.1 1991.33      89 1991.11    98.3 1990.22
   109.9  1988.5   116.4 1988.73   121.5 1989.68   128.4 1990.21   134.6 1989.69
     140 1988.35   143.7  1988.7   149.3 1988.57   151.6 1988.95   153.11989.771
   160.9 1997.67   165.5 2001.46   174.1 2007.85   189.2 2022.01   193.7 2025.82
   221.2 2042.06   243.7 2054.14   258.4 2062.69   273.6 2072.11   278.5 2074.75
#Mann= 4 ,-1 , 0
       0      .1       0   134.6    .045       0   153.1      .1       0
     196      .1       0
#XS Ineff= 2 , 0
           86.04 1991.87
Permanent Ineff=
       F       F
Bank Sta=134.6,153.1
XS Rating Curve= 0 ,0
Exp/Cntr=0.3,0.1

Type RM Length L Ch R = 1 ,2962    ,122.7,122.7,122.7
XS GIS Cut Line= 5
2173120.77196721375663.4886147912172994.57855798375705.453306669
2172984.72178227375707.1343627692172974.86500656375708.815418869
2172850.49652967375749.929759614
#Sta/Elev= 30
       0 2028.17     9.2 2021.92    16.1 2017.69      23 2012.77    29.9 2008.58
    43.8 1997.12    47.2 1994.64    61.1 1987.98    64.5 1987.02    67.9 1986.72
    95.6 1986.72   112.1 1986.11   117.81984.778   119.9 1983.86   123.3 1983.19
     133  1983.6   143.6 1982.66   150.3 1983.25   152.8 1984.25     153 1984.33
   160.5 1987.96   167.5 1994.21   170.8 1996.76   212.1 2026.75   227.6 2039.29
   236.6 2047.62   244.3 2053.63   274.6 2072.68   279.2 2075.95     284 2079.98
#Mann= 6 ,-1 , 0
       0      .1       0  117.77     .06       0   117.8    .045       0
   152.8     .06       0     153      .1       0     198      .1       0
Bank Sta=117.8,152.8
XS Rating Curve= 0 ,0
Exp/Cntr=0.3,0.1

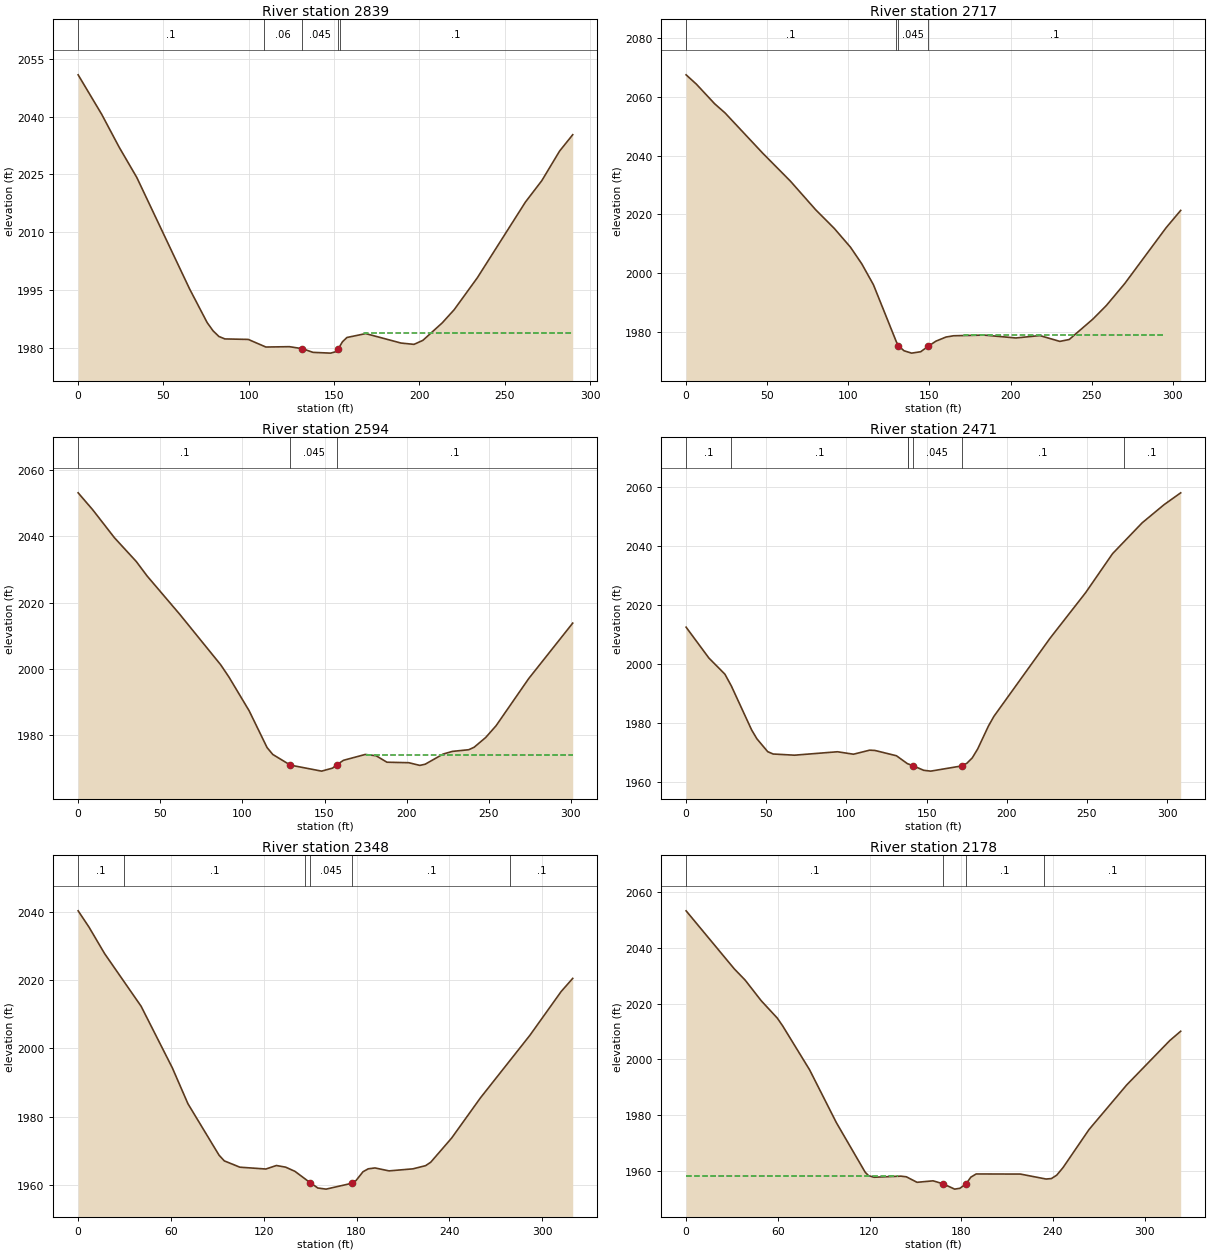
Type RM Length L Ch R = 1 ,2839    ,122.8,122.8,122.8
XS GIS Cut Line= 5
2173095.60509701375546.3721406572173095.60509701375546.372140657
2172957.41673887375589.9661357332172819.22838074375633.560130808
2172819.22838074375633.560130808
#Sta/Elev= 30
       0 2050.82    13.8 2040.59      24  2032.1    34.4  2024.2    65.3 1995.35
    75.6 1986.62    79.1 1984.47    82.5 1983.02      86 1982.39    99.7 1982.26
     110 1980.29   123.8 1980.38   131.4 1979.86   137.6 1978.91   147.9 1978.71
   151.3 1979.11   152.3 1979.75   154.9 1981.66   157.5 1982.76   168.5 1983.77
   189.2 1981.32   196.8 1980.98     202 1982.02   213.3 1986.53   220.3 1989.94
   233.9 1998.23   262.1 2017.86   271.7 2023.41   282.1 2031.06   289.8  2035.3
#Mann= 5 ,-1 , 0
       0      .1       0   108.9     .06       0   131.4    .045       0
   152.3     .06       0   153.3      .1       0
#XS Ineff= 2 , 0
                          167.38         1983.83
Permanent Ineff=
       F       F
Bank Sta=131.4,152.3
XS Rating Curve= 0 ,0
Exp/Cntr=0.3,0.1

Type RM Length L Ch R = 1 ,2717    ,122.8,122.8,122.8
XS GIS Cut Line= 5
2173007.41722775375370.1290376432172933.73303082375473.861472726
2172926.62988985375484.1469045512172919.52674887375494.432336377
2172828.09568672375616.745147899
#Sta/Elev= 30
       0 2067.53     6.3 2064.37    17.6 2057.66      24 2054.54    47.2 2040.83
    64.3 2031.28    79.9 2021.51    91.3 2015.19   101.4 2008.71   108.3 2003.08
   115.5 1995.94   129.6 1976.52   130.91975.155   134.3 1973.46     139 1972.64
   144.6 1973.11   149.2 1974.95     154 1976.72   160.2 1978.12   164.9 1978.56
   183.7 1978.79   203.3 1977.81   218.1 1978.62   230.4 1976.64   236.2 1977.29
   250.9 1984.31   259.1 1988.89   270.4 1996.35   295.9 2015.39   304.9  2021.3
#Mann= 4 ,-1 , 0
       0      .1       0   129.6     .06       0   130.9    .045       0
   149.2      .1       0
#XS Ineff= 1 ,-1
 171.455     295 1978.97
Permanent Ineff=
       F
Bank Sta=130.9,149.2
XS Rating Curve= 0 ,0
Exp/Cntr=0.3,0.1

Type RM Length L Ch R = 1 ,2594    ,123,123,123
XS GIS Cut Line= 5
2172841.19961267 375282.539308212172841.19961267 375282.53930821
2172818.63591056375431.3904724062172796.07220844375580.241636602
2172796.07220844375580.241636602
#Sta/Elev= 30
       0  2053.1     8.9 2047.97    22.1 2039.55    35.4 2032.37      42    2028
    61.9 2016.42    86.8  2001.2    91.8 1997.52   104.1 1987.34     115 1976.25
   118.5 1974.15   129.21970.936   148.2 1969.12   154.9 1970.03   157.3 1970.97
   161.5 1972.38   174.8 1974.15   181.4 1973.76     188 1971.81   201.3 1971.66
     208 1970.85   211.3 1971.21   222.2 1974.27   227.9 1975.08   237.8 1975.58
   241.1 1976.33   248.1 1979.26   254.4 1982.79   274.3 1997.04   301.1 2013.79
#Mann= 3 , 0 , 0
       0      .1       0   129.2    .045       0   157.3      .1       0
#XS Ineff= 2 , 0
                          175.53         1974.11
Permanent Ineff=
       F       F
Bank Sta=129.2,157.3
XS Rating Curve= 0 ,0
Exp/Cntr=0.3,0.1

Type RM Length L Ch R = 1 ,2471    ,122.3,122.3,122.3
XS GIS Cut Line= 5
 2172721.2029616375310.2465814922172695.57726229375439.034050921
 2172700.8261862375459.0664238552172707.19118448375486.539292608
2172678.58143567375611.611497012
#Sta/Elev= 30
       0  2012.5    14.2 2002.07    24.2  1996.6    28.2 1992.64    40.9 1977.71
    44.2 1974.71    50.9 1970.39    54.3  1969.6    67.6  1969.2    94.4 1970.36
   104.4 1969.53   114.5  1970.9   117.8  1970.8   131.2 1969.01     138 1966.35
   141.4 1965.67   148.2 1964.09   152.6 1963.81   171.8 1965.56   175.1 1966.45
   178.5 1968.29   181.9 1971.34   188.6 1979.08     192 1982.34     227 2008.75
   249.2 2024.17     266 2037.36   284.5 2047.81   298.2 2053.96   308.5 2057.94
#Mann= 7 ,-1 , 0
       0      .1       0      28      .1       0   138.5     .06       0
   138.5     .06       0   141.4    .045       0   171.8      .1       0
     273      .1       0
Bank Sta=141.4,171.8
XS Rating Curve= 0 ,0
Exp/Cntr=0.3,0.1

Type RM Length L Ch R = 1 ,2348    ,170.3,170.3,170.3
XS GIS Cut Line= 5
  2172654.166923375251.6349552792172624.36280459375382.451120764
2172604.80792826375399.7802670522172586.04425111375418.537525493
2172555.44893352375547.925578826
#Sta/Elev= 30
       0 2040.43       7 2035.66    17.1 2027.87    40.7 2012.41    60.9 1994.31
      71 1983.76    91.1 1968.66    94.5 1966.98   104.6 1965.12   121.4 1964.59
   128.2 1965.62   134.2 1965.13   140.2  1963.9   150.1 1960.55     155 1959.01
   160.3 1958.68   177.3 1960.43   179.6 1961.16   184.2 1963.79   187.6 1964.65
     192  1964.9     201 1964.04   216.5 1964.64   224.7 1965.58     228 1966.59
   241.5 1973.68   260.1 1985.47   292.1 2003.86   312.3 2016.71   319.8 2020.58
#Mann= 6 ,-1 , 0
       0      .1       0   29.63      .1       0   146.5     .06       0
   150.1    .045       0   177.3      .1       0  279.51      .1       0
Bank Sta=150.1,177.3
XS Rating Curve= 0 ,0
Exp/Cntr=0.3,0.1

Type RM Length L Ch R = 1 ,2178    ,160.2,160.2,160.2
XS GIS Cut Line= 5
2172509.12676539  375189.70171572172509.12676539  375189.7017157
 2172450.8783561375340.6551042532172392.62994681375491.608492806
2172392.62994681375491.608492806
#Sta/Elev= 30
       0 2053.31    31.5 2032.47    38.6 2028.44    49.1 2021.04    59.7 2014.75
    63.2 2011.95    80.8 1996.19    98.3 1977.23   117.2 1959.37   119.4 1958.16
     123  1957.6   140.5 1957.99   144.1 1957.76   151.1 1955.78   161.6 1956.31
     168 1955.27   175.7 1953.33   179.2 1953.64   183.2 1955.25   186.3 1957.63
   189.8 1958.78   218.7 1958.74   235.5 1956.96     239 1957.12   242.5 1958.35
   246.6 1961.05   263.6 1974.72   288.2 1990.72   316.4 2006.67   323.6 2010.05
#Mann= 4 ,-1 , 0
       0      .1       0     168    .045       0   183.2      .1       0
  234.19      .1       0
#XS Ineff= 2 , 0
          138.81 1957.97  192.87         1958.75
Permanent Ineff=
       F       F
Bank Sta=168,183.2
XS Rating Curve= 0 ,0
Exp/Cntr=0.3,0.1

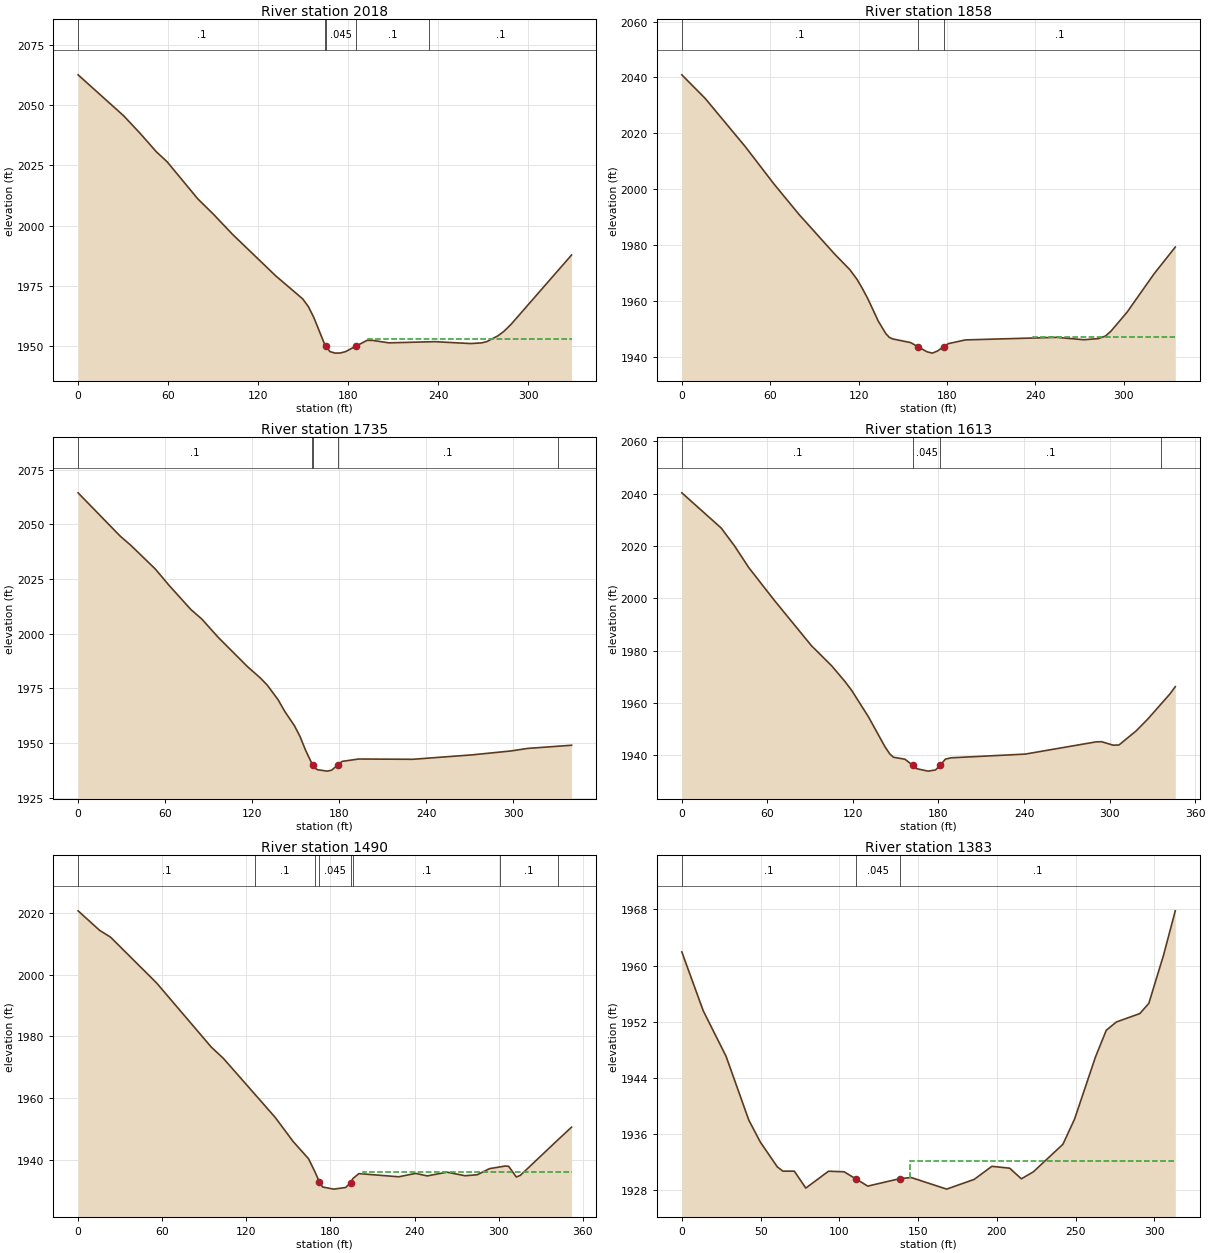
Type RM Length L Ch R = 1 ,2018    ,160.2,160.2,160.2
XS GIS Cut Line= 5
2172384.78310107 375116.160412952172315.12187076375264.651841873
2172312.56867678375272.2344805442172310.01548279375279.817119216
2172246.19266924 375414.47566606
#Sta/Elev= 30
       0 2062.48    30.4  2045.5    41.3 2038.28    52.1 2030.65    59.4 2026.43
    79.8  2011.1    90.6 2004.49   102.9 1996.43   131.8 1979.17   149.8 1969.62
   153.6 1966.37   157.2  1961.9   164.4 1950.81     165  1950.2   167.9 1947.81
   171.4 1947.17   174.8 1947.22   178.3 1947.79   185.5 1950.15   192.7 1952.47
   196.3 1952.45   207.2 1951.43   237.8 1951.92   261.7 1951.14     269 1951.41
   272.6 1951.96   279.9 1954.34   283.6 1956.03   288.5 1958.98     329 1987.82
#Mann= 5 ,-1 , 0
       0      .1       0   164.4     .06       0     165    .045       0
   185.5      .1       0     234      .1       0
#XS Ineff= 2 , 0
                          193.27          1952.9
Permanent Ineff=
       F       F
Bank Sta=165,185.5
XS Rating Curve= 0 ,0
Exp/Cntr=0.3,0.1

Type RM Length L Ch R = 1 ,1858    ,122.6,122.6,122.6
XS GIS Cut Line= 5
2172237.12238967375070.4661413092172237.12238967375070.466141309
 2172161.9854255375220.1141941552172086.84846133375369.762247002
2172086.84846133375369.762247002
#Sta/Elev= 30
       0 2040.94    15.8 2032.53    43.1 2015.23    62.6 2001.84    79.7  1990.9
   103.9 1976.71     114 1971.26   118.9 1967.76   122.3 1964.72   126.2 1960.89
   133.3 1952.86   138.4 1948.39   140.8 1947.01   143.3 1946.43   155.3 1945.14
   160.11943.713   166.3 1941.87     170 1941.37   173.7 1942.17   177.6 1943.71
     181 1944.78   192.5  1946.1   254.4 1947.02   272.9 1946.16   282.6 1946.56
   287.5 1947.47   291.2  1949.2   302.2 1956.03   320.5 1969.74   334.9 1979.31
#Mann= 3 ,-1 , 0
       0      .1       0   160.1    .045       0   177.6      .1       0
#XS Ineff= 2 , 0
                          238.67         1947.03
Permanent Ineff=
       F       F
Bank Sta=160.1,177.6
XS Rating Curve= 0 ,0
Exp/Cntr=0.3,0.1

Type RM Length L Ch R = 1 ,1735    ,122.6,122.6,122.6
XS GIS Cut Line= 5
2172148.12072393374996.7416261162172070.41415297375137.771164473
2172066.66738611 375145.955447772172062.92061925375154.139731068
2171985.21404829375295.169269424
#Sta/Elev= 30
       0 2064.35    29.1 2044.53    36.2 2040.47    53.1 2029.63    62.5 2022.24
    77.8    2011    85.3 2006.68    96.5 1998.38   116.9 1984.86   125.5 1979.85
   130.3 1976.57   137.8 1969.87   142.4 1964.52     149 1958.06   152.8 1953.24
   156.9 1946.55     161 1940.85   161.8 1940.04   163.9 1938.34     165 1937.89
   171.7 1937.25   174.7 1937.69     179 1940.11     182 1941.71   193.3 1942.78
   230.7 1942.66   271.9  1944.7   298.2 1946.46   309.7 1947.62     340 1949.07
#Mann= 5 ,-1 , 0
       0      .1       0     161     .06       0   161.8    .045       0
     179      .1       0     331      .1       0
Bank Sta=161.8,179
XS Rating Curve= 0 ,0
Exp/Cntr=0.3,0.1

Type RM Length L Ch R = 1 ,1613    ,122.7,122.7,122.7
XS GIS Cut Line= 5
2172052.88063102374967.8956402972172052.88063102374967.895640297
2171951.08658998375107.8417703142171849.29254894375247.787900331
2171849.29254894375247.787900331
#Sta/Elev= 30
       0 2040.34    27.6 2026.89      37 2020.02    46.9  2011.8    65.1 1999.09
      91 1981.84   105.1 1974.21   114.5 1968.15   119.2 1964.74   130.9 1954.69
   142.6 1943.14   145.9  1940.5   148.4 1939.25   156.5 1938.48     1621936.133
   164.6 1934.88   172.7 1933.93   177.9 1934.37   181.21936.156   184.9 1938.53
   188.9 1939.02   240.8 1940.44   290.6 1945.12   294.4 1945.18   302.5 1943.86
   306.6 1943.92   318.6 1949.29   326.9 1953.89   342.3 1963.42   346.1 1966.22
#Mann= 4 ,-1 , 0
       0      .1       0     162    .045       0   181.2      .1       0
  335.96     .06       0
Bank Sta=162,181.2
XS Rating Curve= 0 ,0
Exp/Cntr=0.3,0.1

Type RM Length L Ch R = 1 ,1490    ,107.2,107.2,107.2
XS GIS Cut Line= 5
2171993.45279772374881.4926131742171882.89237231375009.296452496
2171871.85680065375017.0709860122171860.82122899375024.845519528
2171757.14018236 375141.39249647
#Sta/Elev= 30
       0 2020.78    15.3 2014.46    23.2 2012.21      56 1997.36      95 1976.53
   103.7 1972.83   140.7 1953.64   153.4 1945.86   164.4 1940.26     169 1935.97
   172.1 1932.77   174.4 1931.09   182.4 1930.39   190.9 1930.93   194.5 1932.53
     196 1933.81   200.3 1935.43   228.7  1934.4   240.8  1935.5   249.1 1934.68
   263.2  1935.9     276 1934.74   284.7 1935.05   293.5 1937.05   304.8  1937.9
   307.2 1937.78   312.6 1934.33   315.5 1934.87     342 1946.28     352 1950.51
#Mann= 8 ,-1 , 0
       0      .1       0     126      .1       0     169      .1       0
   172.1    .045       0   194.5      .1       0     196      .1       0
     301      .1       0     342      .1       0
#XS Ineff= 2 , 0
                          203.12         1935.99
Permanent Ineff=
       F       F
Bank Sta=172.1,194.5
XS Rating Curve= 0 ,0
Exp/Cntr=0.3,0.1

Type RM Length L Ch R = 1 ,1383    ,57.4,57.4,57.4
XS GIS Cut Line= 3
2171897.41309456374885.9633690992171806.57576561374927.809779064
2171702.98038484375114.077335612
#Sta/Elev= 30
       0 1961.96    13.6 1953.57    28.1 1947.09    42.5 1938.02    49.8 1934.89
    60.6 1931.35    64.2 1930.74    71.4 1930.74    78.7 1928.33    93.1 1930.73
     103 1930.65   110.5 1929.64     118 1928.61   138.3 1929.67   145.6 1929.83
   168.1 1928.18   185.6 1929.57   196.8 1931.43   208.1 1931.16   215.5 1929.65
   223.1 1930.64   241.9 1934.57   249.3 1938.17   262.6 1947.03   269.4  1950.8
   275.8 1951.98   290.7 1953.18   296.4 1954.63   305.7 1961.46   313.2 1967.81
#Mann= 3 , 0 , 0
       0      .1       0   110.5    .045       0   138.3      .1       0
#XS Ineff= 2 , 0
                          145.12         1932.16
Permanent Ineff=
       F       F
Bank Sta=110.5,138.3
XS Rating Curve= 0 ,0
Exp/Cntr(USF)=0,0
Exp/Cntr=0.3,0.1

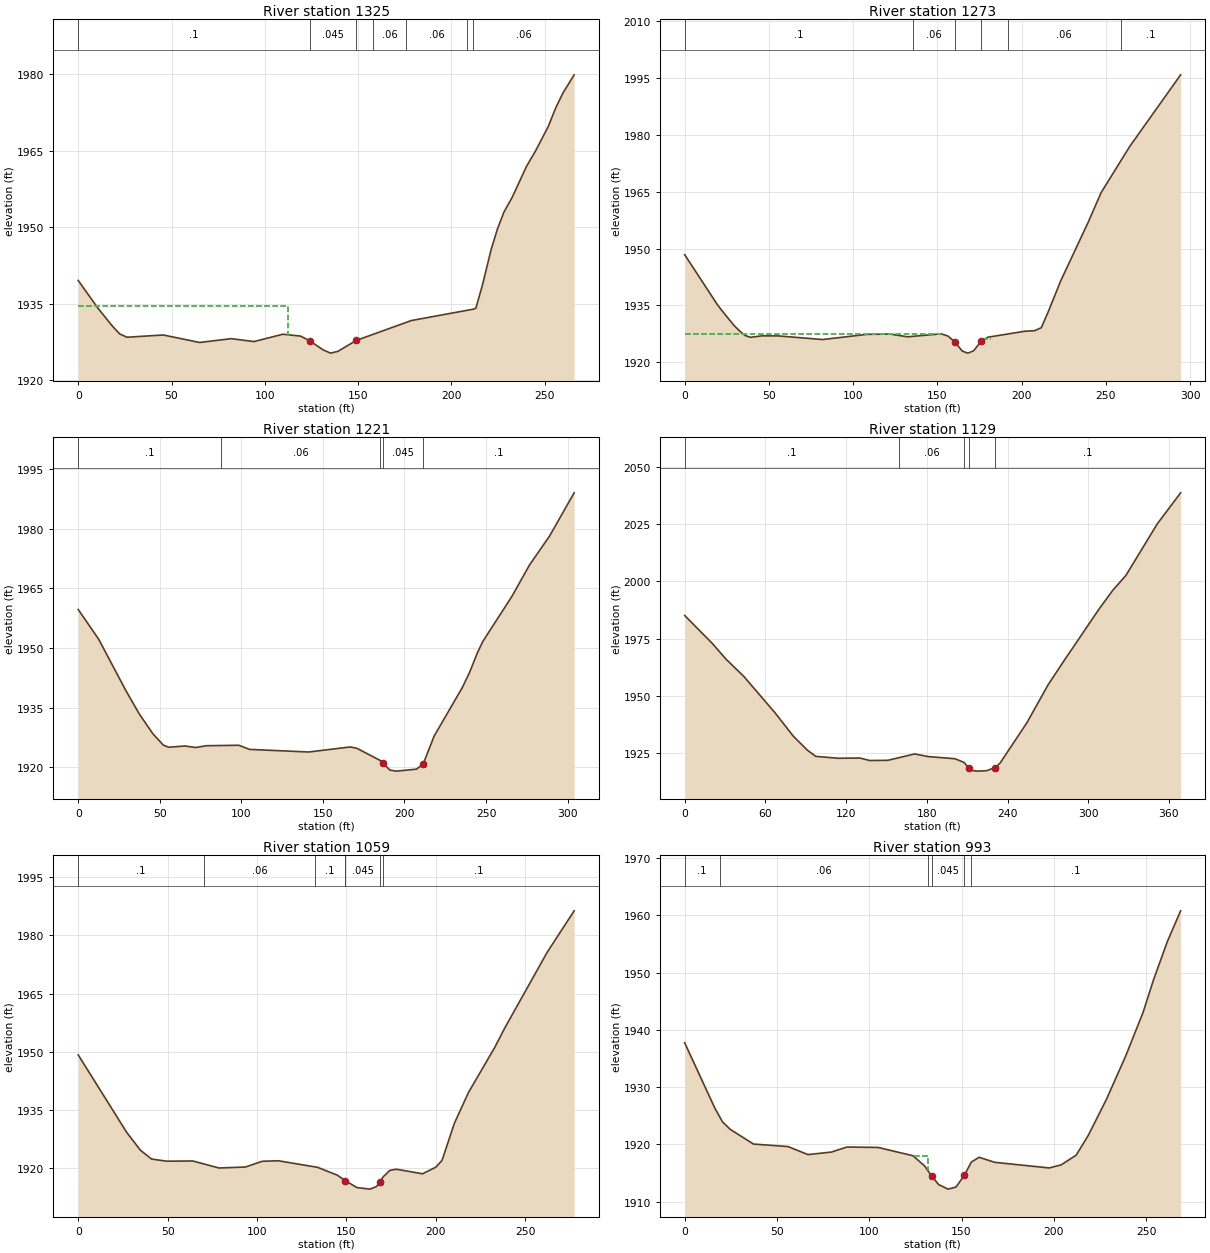
Type RM Length L Ch R = 1 ,1325    ,52.4,52.4,52.4
XS GIS Cut Line= 2
2171867.70663442374837.0251740072171643.72391066374980.215964319
#Sta/Elev= 30
       0 1939.52    10.6 1934.07    18.4 1930.53    22.3 1929.01    26.2 1928.38
    45.6 1928.82    65.1 1927.35      82  1928.1    94.2 1927.53   109.7 1928.97
   119.2  1928.6     124 1927.69   131.3 1925.89   135.2 1925.26   139.1 1925.59
     149 1927.75   178.6 1931.66   211.8 1933.89   213.1 1934.06   216.6 1938.55
   221.3 1945.58   224.8 1949.75   228.2 1952.96   232.6 1955.84   240.3 1961.94
   245.1 1964.94     252 1969.79   255.9 1973.38   259.8 1976.31   265.8 1979.88
#Mann= 7 ,-1 , 0
       0      .1       0     124    .045       0     149     .06       0
   157.8     .06       0   175.9     .06       0  208.59     .06       0
   211.8     .06       0
#XS Ineff= 2 , 0
          112.18 1934.47
Permanent Ineff=
       F       F
Bank Sta=124,149
XS Rating Curve= 0 ,0
Exp/Cntr=0.5,0.3

Type RM Length L Ch R = 1 ,1273    ,51.5,51.5,51.5
XS GIS Cut Line= 3
2171881.43098989374835.1752233232171776.39459156374831.284986347
2171619.67361627374937.432880959
#Sta/Elev= 30
       0 1948.38    19.4 1935.18    22.7 1933.28    29.2 1929.73    32.5 1928.26
    35.8 1927.03    39.1 1926.54    45.7 1926.93    55.5 1926.92    81.8 1925.96
   108.6 1927.34   121.9  1927.4   132.4 1926.68   152.2 1927.46   156.2 1926.91
   160.2 1925.41   164.8 1922.91   168.1 1922.37   171.5 1922.98     176 1925.47
     180 1926.58   202.2 1928.17   207.7 1928.29   211.7 1929.09   215.6 1933.05
   223.3 1941.53   239.4 1956.81   247.3 1964.84   264.3 1977.03   294.4 1995.88
#Mann= 6 ,-1 , 0
       0      .1       0   135.8     .06       0   160.2    .045       0
     176     .06       0   191.7     .06       0  258.85      .1       0
#XS Ineff= 2 ,-1
       0  152.18 1927.52  176.91  182.11 1925.99
Permanent Ineff=
       F       F
Bank Sta=160.2,176
XS Rating Curve= 0 ,0
Exp/Cntr=0.5,0.3

Type RM Length L Ch R = 1 ,1221    ,92.2,92.2,92.2
XS GIS Cut Line= 3
2171904.06498692 374808.370526422171750.12275232  374791.1423341
2171630.08115423374879.506288254
#Sta/Elev= 30
       0 1959.71    12.6 1952.19    29.1 1939.39    37.4 1933.45    45.6 1928.53
    52.2 1925.57    55.5 1925.05    65.4 1925.37      72 1924.98    78.6 1925.43
    98.4 1925.55     105 1924.51   141.3 1923.85   166.7 1925.12   170.7 1924.81
     185 1921.75     187 1920.98   191.1 1919.29   195.2 1919.04   207.4 1919.54
   211.5 1920.87   218.2 1927.87   235.5  1940.1     240 1943.98   244.8 1948.91
   248.1 1951.72     266 1963.11   276.6 1970.88   288.9 1978.17     304 1989.06
#Mann= 5 ,-1 , 0
       0      .1       0   87.68     .06       0     185     .06       0
     187    .045       0   211.5      .1       0
Bank Sta=187,211.5
XS Rating Curve= 0 ,0
Exp/Cntr=0.5,0.3

Type RM Length L Ch R = 1 ,1129    ,69.9,69.9,69.9
XS GIS Cut Line= 5
2171957.70340635 374770.940786942171957.70340635 374770.94078694
2171776.73035277374735.8066465482171595.75729918374700.672506155
2171595.75729918374700.672506155
#Sta/Elev= 30
       0 1985.15    20.6 1972.91    30.6 1966.16      44 1958.51    67.4 1942.47
    80.7 1932.46    91.1 1926.37    97.4 1923.61   114.1 1922.77   130.3 1922.87
   137.5  1921.8   150.9 1921.86     171 1924.65     181 1923.51     201 1922.56
   207.7 1920.95   211.1 1918.66   214.2 1917.38   217.8 1917.15   224.4 1917.33
     231 1918.73   234.5 1920.68   254.5 1938.36   270.2 1954.88   281.4 1964.83
     308 1987.91   318.3 1996.19     328 2002.63   351.4 2025.23   368.7 2038.74
#Mann= 5 ,-1 , 0
       0      .1       0   159.1     .06       0   207.7     .06       0
   211.1    .045       0     231      .1       0
Bank Sta=211.1,231
XS Rating Curve= 0 ,0
Exp/Cntr=0.3,0.1

Type RM Length L Ch R = 1 ,1059    ,66.2,66.2,66.2
XS GIS Cut Line= 2
2171909.54249534374735.5502898912171661.59657448374611.172189065
#Sta/Elev= 30
       0 1949.17    27.1 1929.19    34.8 1924.58      41  1922.3    49.5 1921.75
    64.1  1921.8    78.8 1919.99    93.5 1920.24   102.9 1921.72   111.9 1921.86
   133.9 1920.16   144.9 1918.15   149.3 1916.74   155.9 1914.94   163.2 1914.54
   166.9 1915.22   168.9 1916.49   170.6 1917.71   174.3 1919.37   177.9 1919.68
   192.6  1918.5     200 1920.19   203.1 1921.74   203.6 1922.08   210.4 1931.52
   218.3 1939.47     233 1951.11   238.6 1956.11   262.3 1975.62   277.4 1986.33
#Mann= 7 ,-1 , 0
       0      .1       0   70.36     .06       0  132.56      .1       0
     149     .06       0   149.3    .045       0   168.9     .06       0
   170.6      .1       0
#XS Ineff= 2 , 0
                          177.87         1919.66
Permanent Ineff=
       F       F
Bank Sta=149.3,168.9
XS Rating Curve= 0 ,0
Exp/Cntr=0.5,0.3

Type RM Length L Ch R = 1 ,993     ,34.8,34.8,34.8
XS GIS Cut Line= 3
2171907.51679337 374694.631110142171748.70175909374566.606745772
2171684.28443652374560.934780262
#Sta/Elev= 30
       0 1937.74    16.3 1926.37    20.5 1923.94    24.7 1922.62    37.3 1920.06
      56 1919.62    66.8 1918.22    79.5 1918.66    87.9 1919.54   104.8 1919.47
   123.7 1918.02     130 1916.24   133.91914.446   137.6 1912.99   142.7 1912.19
     147 1912.55   151.6 1914.64   155.3 1916.91   159.5 1917.75     168 1916.87
   197.5 1915.89     204 1916.43   212.1 1918.12   218.7 1921.59   228.5 1927.86
     239 1935.48   248.3    1943   254.1 1948.81   261.5 1955.41   268.7 1960.79
#Mann= 6 ,-1 , 0
       0      .1       0   18.95     .06       0  131.88      .1       0
   133.9    .045       0   151.6     .06       0   155.1      .1       0
#XS Ineff= 2 ,-1
  124.13  131.62 1917.98  159.27   268.7 1917.69
Permanent Ineff=
       F       F
Bank Sta=133.9,151.6
XS Rating Curve= 0 ,0
Exp/Cntr=0.5,0.3

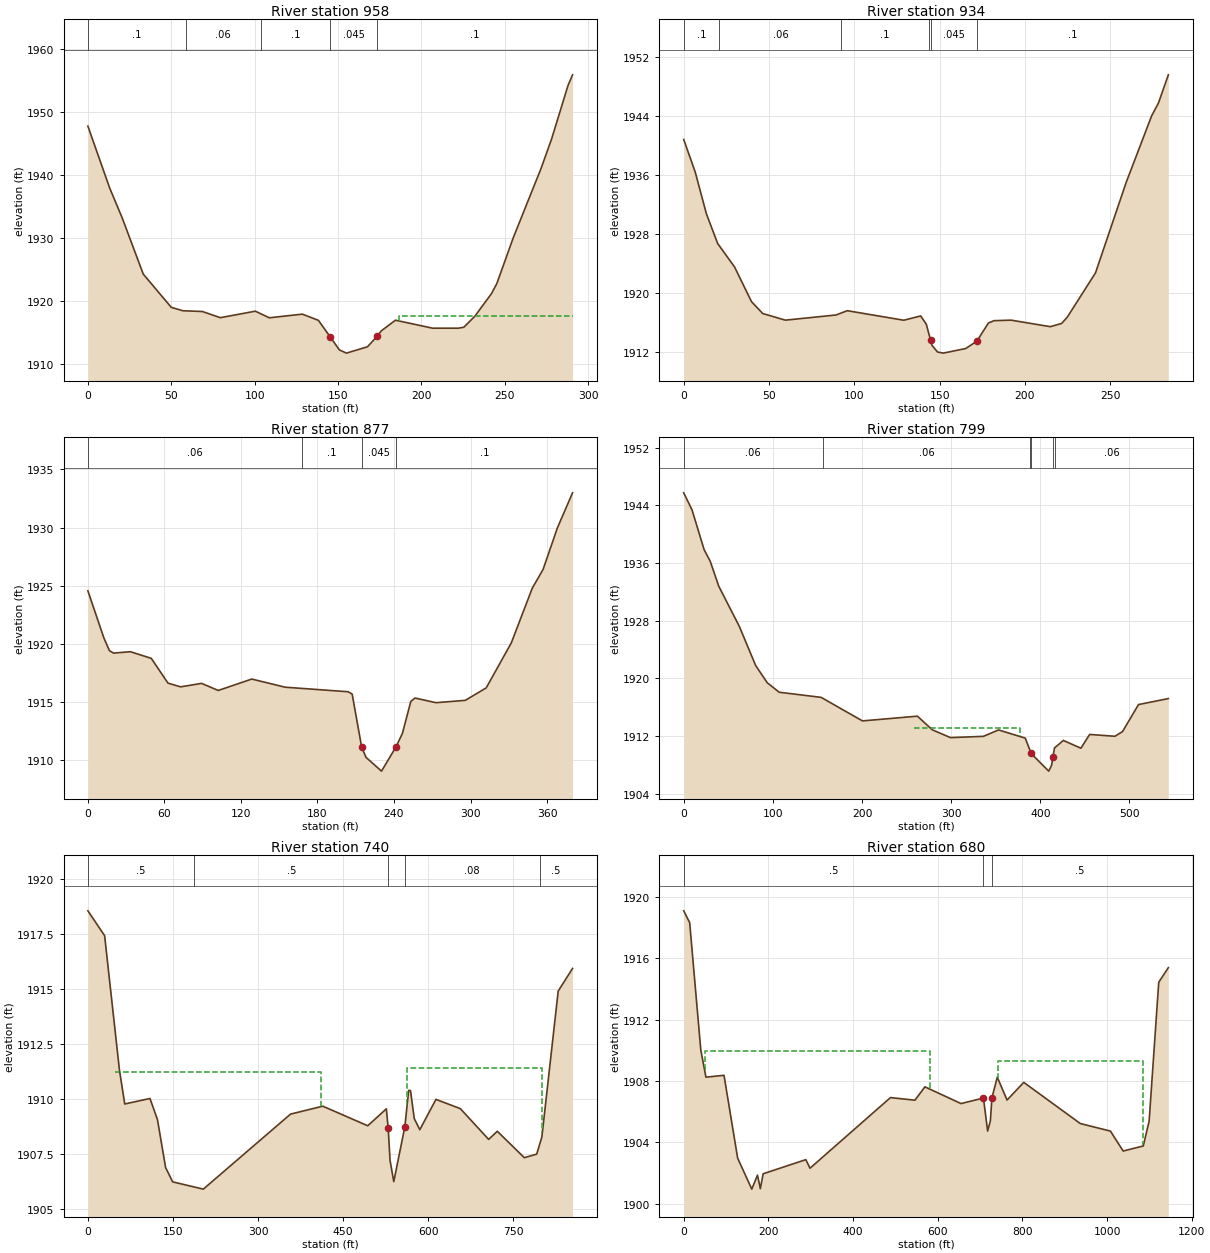
Type RM Length L Ch R = 1 ,958     ,24.4,24.4,24.4
XS GIS Cut Line= 3
2171930.60979581374669.5124057392171781.11299058374549.995989635
2171682.25873455374541.893181764
#Sta/Elev= 30
       0 1947.73      13 1937.95    20.6 1933.14    33.2 1924.24      50 1918.96
    56.9 1918.42    68.6  1918.3    79.4 1917.32   100.4 1918.35   108.8  1917.3
   128.6 1917.88   138.2  1916.9   145.21914.298   150.8  1912.2     155 1911.69
   167.6 1912.69   173.6 1914.41   175.9 1915.22   184.4 1916.92   206.7 1915.65
   222.1 1915.65   225.4  1915.8     232 1917.54   241.9  1921.1   245.2 1922.73
     255 1929.97   271.7    1941   278.1 1945.74   287.9  1954.2   290.6 1955.88
#Mann= 5 ,-1 , 0
       0      .1       0   58.81     .06       0  103.54      .1       0
   145.2    .045       0   173.6      .1       0
#XS Ineff= 2 , 0
                          186.41         1917.61
Permanent Ineff=
       F       F
Bank Sta=145.2,173.6
XS Rating Curve= 0 ,0
Exp/Cntr=0.5,0.3

Type RM Length L Ch R = 1 ,934     ,56.7,56.7,56.7
XS GIS Cut Line= 2
2171963.83130808374566.6067457722171681.85359416374532.169812318
#Sta/Elev= 30
       0 1940.78     6.7 1936.41    13.3 1930.73    19.9 1926.71    29.8 1923.54
    39.7 1918.86    46.3 1917.24    59.6 1916.34    89.3 1917.04    95.9 1917.62
     129 1916.33   138.9 1916.91   142.2  1915.8   144.7 1913.65   145.5 1912.95
   148.8 1912.03   152.1 1911.88   165.3  1912.5   171.9 1913.51   178.6 1915.95
   181.9 1916.27   191.9 1916.34   214.9 1915.46   221.5 1915.89   224.8 1916.73
   241.4 1922.74   259.4 1934.99   274.3 1943.98   278.3 1945.72   284.1 1949.53
#Mann= 6 ,-1 , 0
       0      .1       0   20.92     .06       0   92.42      .1       0
   143.6     .06       0   144.7    .045       0   171.9      .1       0
#XS Ineff= 2 , 0
                          191.79         1916.31
Permanent Ineff=
       F       F
Bank Sta=144.7,171.9
XS Rating Curve= 0 ,0
Exp/Cntr=0.5,0.3

Type RM Length L Ch R = 1 ,877     ,78.1,78.1,78.1
XS GIS Cut Line= 2
2172029.81886365374499.9453810822171650.04487745374488.138935916
#Sta/Elev= 30
       0 1924.57    12.5 1920.53    16.9 1919.43    20.1 1919.22    33.3 1919.34
    49.7 1918.77    62.8 1916.64    72.7 1916.32    89.1 1916.62   102.2 1916.01
   128.5 1916.99   154.7 1916.29     204  1915.9   207.2  1915.7   214.6 1911.18
     218 1910.27   230.2 1909.08   241.7 1911.18   241.7 1911.19   246.6 1912.32
   253.2 1915.07   256.5 1915.36   272.9 1914.96   295.9 1915.16   312.3 1916.23
     332  1920.1   348.4 1924.79   356.9 1926.41   368.1 1929.97     380 1932.99
#Mann= 4 ,-1 , 0
       0     .06       0  167.65      .1       0   214.6    .045       0
   241.7      .1       0
Bank Sta=214.6,241.7
XS Rating Curve= 0 ,0
Exp/Cntr=0.5,0.3

Type RM Length L Ch R = 1 ,799     ,58.8,58.8,58.8
XS GIS Cut Line= 4
2172179.64862556374502.5356027012171816.29485633374417.836234215
2171730.10951596374416.9337699182171659.63484379374463.193864303
#Sta/Elev= 30
       0 1945.74     9.3 1943.38    22.9 1937.85    29.7 1936.25    39.3 1932.78
    62.5 1927.17    80.7 1921.77    93.7 1919.38   107.1 1918.06   154.1 1917.35
   200.5 1914.08   262.1 1914.74   278.9 1912.84   299.2 1911.76   336.2 1911.94
   353.1 1912.83   383.1 1911.69   388.8 1909.86   389.7 1909.56   409.4 1907.11
   412.6 1907.91   414.21909.083   415.9 1910.33   425.8 1911.37   445.5 1910.29
   455.3  1912.2   483.7 1911.95   492.2  1912.6   510.1 1916.35   543.6 1917.18
#Mann= 6 ,-1 , 0
       0     .06       0  156.12     .06       0   388.8     .06       0
   389.7    .045       0   414.2     .06       0   415.9     .06       0
#XS Ineff= 1 ,-1
   257.8   376.9 1913.16
Permanent Ineff=
       F
Bank Sta=389.7,414.2
XS Rating Curve= 0 ,0
Exp/Cntr=0.5,0.3

Type RM Length L Ch R = 1 ,740     ,60.4,60.4,60.4
XS GIS Cut Line= 6
2172320.10587817 374450.871110962171892.46651846374361.561392567
2171835.66519275374359.600828092 2171723.5133451374359.391601315
2171652.62085151374370.9022948842171480.16817591374411.220232529
#Sta/Elev= 30
       0 1918.56    29.5 1917.43    55.7 1911.31      65 1909.78   109.5 1910.03
   122.7 1909.07   137.1 1906.89   149.5 1906.24   203.6 1905.91   357.4 1909.32
   414.3 1909.68   493.6 1908.79   526.4 1909.56   529.6  1908.7   532.9 1907.22
   539.5 1906.25     5591908.743   565.8  1910.4     569 1910.39   575.6 1909.12
   585.4 1908.61   613.9 1909.99   656.8 1909.57   706.9 1908.17   722.1 1908.54
   769.7 1907.34   791.6  1907.5   800.7 1908.28   829.5 1914.91   854.8 1915.94
#Mann= 5 ,-1 , 0
       0      .5       0   187.9      .5       0   529.6    .045       0
     559     .08       0   796.8      .5       0
#XS Ineff= 2 ,-1
   47.18  411.161911.218  563.07   801.5 1911.42
Permanent Ineff=
       F       F
Bank Sta=529.6,559
XS Rating Curve= 0 ,0
Exp/Cntr=0.3,0.1

Type RM Length L Ch R = 1 ,680     ,98,98,98
XS GIS Cut Line= 6
2172488.80798991374418.1701244392171924.11139311374301.435854183
2171874.20806449374295.5856172612171696.55391457374303.436169205
2171684.15604602374304.9975942562171364.13769776374375.040761188
#Sta/Elev= 30
       0 1919.08    14.1 1918.31    40.3 1910.03    52.5 1908.25    95.2 1908.37
   127.4 1902.98   160.8 1900.96   174.3 1901.87     181 1900.99   187.7 1901.96
   288.5 1902.88   298.3 1902.32   488.4 1906.92   546.2 1906.75   569.7 1907.62
   655.1 1906.53     708 1906.89   717.9 1904.74   724.4  1905.4   728.1 1906.91
   740.7 1908.25   763.8 1906.76   803.3 1907.91   936.8 1905.23  1007.9 1904.74
  1038.1 1903.44  1085.6 1903.77  1099.4 1905.39  1122.1 1914.43  1144.8 1915.38
#Mann= 3 , 0 , 0
       0      .5       0     708    .045       0   728.1      .5       0
#XS Ineff= 2 ,-1
   49.32  581.441909.985  742.93  1085.9 1909.28
Permanent Ineff=
       F       F
Bank Sta=708,728.1
XS Rating Curve= 0 ,0
Exp/Cntr=0.3,0.1