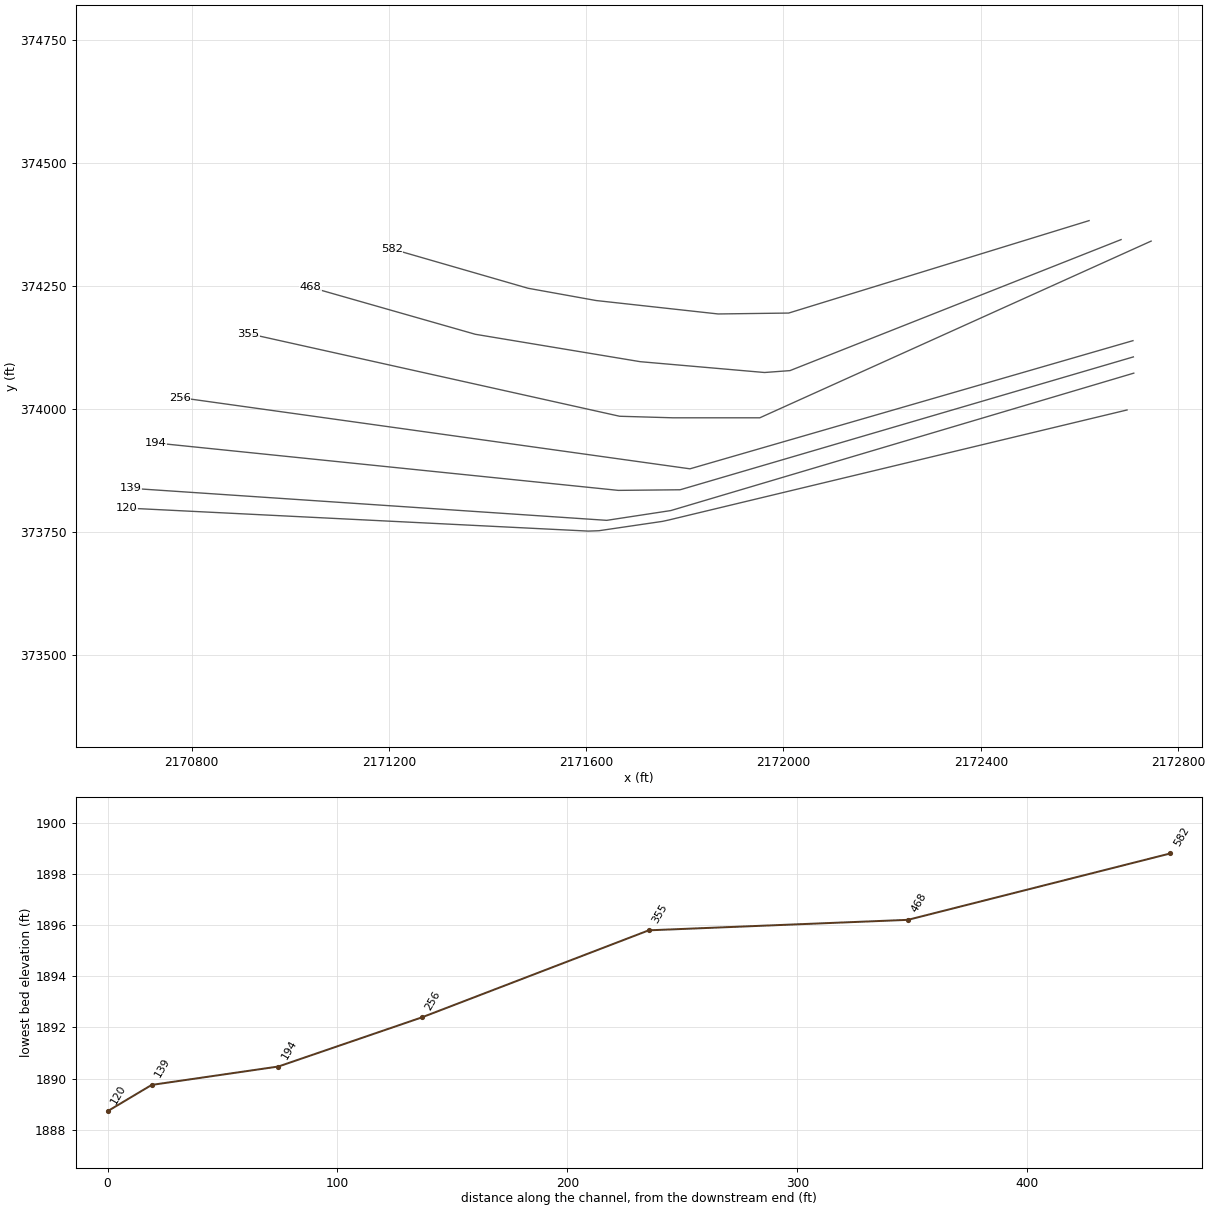
HEC-RAS study GRBRRVTR5.prj: GRBRRVTR5

--- GRBRRVTR5.g02 (geometry) --- (continued)

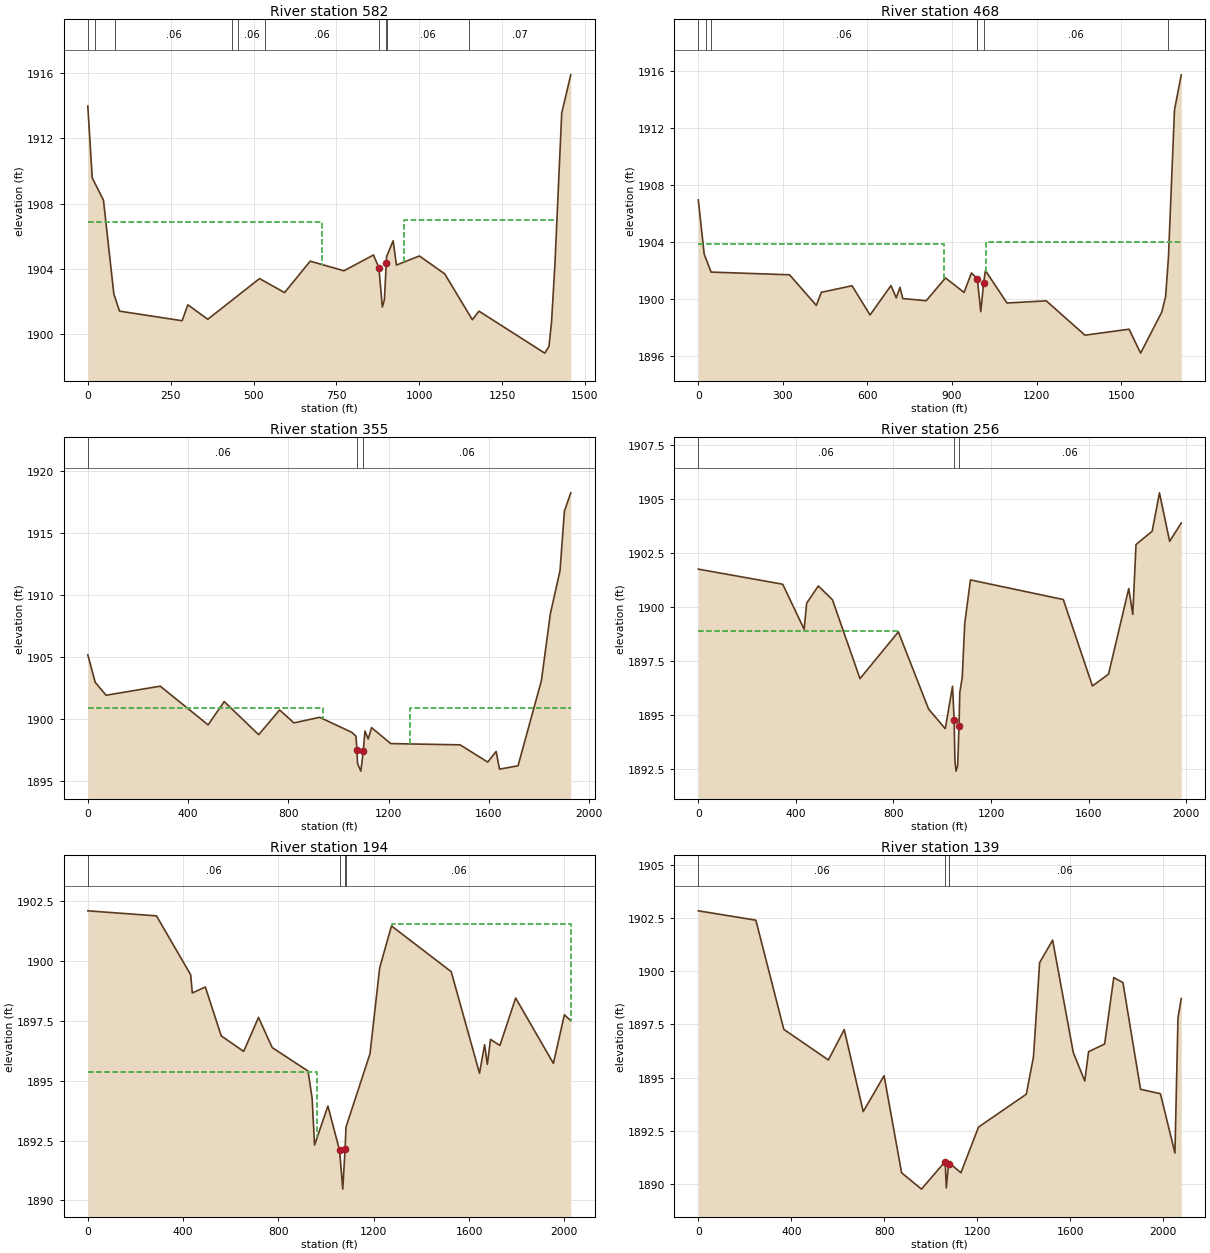
Type RM Length L Ch R = 1 ,582     ,114.2,114.2,114.2
XS GIS Cut Line= 6
2172619.50524785374382.9042514672172010.51982025374194.844694761
2171867.48049941374193.0068283822171620.14055694374220.324556726
2171482.25053843374245.2747403662171205.88807105 374325.36888141
#Sta/Elev= 30
       0 1913.99    13.3 1909.58    47.2 1908.21    78.5 1902.45    95.7 1901.39
   284.6  1900.8   301.7 1901.78     362 1900.89   518.1 1903.39   593.6 1902.53
     671 1904.46   772.7 1903.87   861.9 1904.84   878.21904.055   888.6 1901.64
   894.8 1902.08   900.5 1904.36   901.4 1904.74   921.2 1905.71   931.1 1904.22
  1000.4 1904.78  1076.8 1903.68  1160.2 1900.86  1180.1 1901.39  1378.6 1898.81
  1391.3 1899.22  1399.1 1900.73  1409.3 1904.27  1429.8 1913.57  1457.1 1915.91
#Mann= 10 ,-1 , 0
       0     .07       0   22.46     .07       0   81.43     .06       0
  434.67     .06       0  453.56     .06       0   535.4     .06       0
   878.2    .045       0   900.5     .06       0   901.4     .06       0
  1149.3     .07       0
#XS Ineff= 2 ,-1
       0  706.31 1906.87  954.06  1415.8    1907
Permanent Ineff=
       F       F
Bank Sta=878.2,900.5
XS Rating Curve= 0 ,0
Exp/Cntr=0.3,0.1

Type RM Length L Ch R = 1 ,468     ,112.7,112.7,112.7
XS GIS Cut Line= 6
 2172684.3391106374344.2923011372172013.12363536374077.751483401
2171961.53809009374073.9092791312171709.68282101374095.915782926
2171375.38247768 374151.645073232171040.99263364374247.382518774
#Sta/Elev= 30
       0 1906.97    20.9 1903.16    45.4  1901.9   323.7 1901.71   418.8 1899.56
   436.4 1900.48   545.4 1900.94   609.4 1898.89   683.5 1900.95   702.4 1900.09
   715.3 1900.83   725.5 1900.04   808.5 1899.89   877.1 1901.49   942.9 1900.47
   969.1 1901.84   989.81901.447  1002.2 1899.12  1012.1 1901.11  1018.7 1902.01
  1095.1 1899.73  1234.6 1899.88  1371.9 1897.47  1528.3 1897.89  1569.3 1896.21
  1644.3 1899.09    1658 1900.18    1668 1902.92  1689.4 1913.28  1713.5 1915.75
#Mann= 7 ,-1 , 0
       0     .06       0   26.33     .06       0    45.4     .06       0
  989.79     .06       0   989.8    .045       0  1012.1     .06       0
    1668     .06       0
#XS Ineff= 2 , 0
          870.27 1903.85 1021.62         1904.03
Permanent Ineff=
       F       F
Bank Sta=989.8,1012.1
XS Rating Curve= 0 ,0
Exp/Cntr=0.3,0.1

Type RM Length L Ch R = 1 ,355     ,98.8,98.8,98.8
XS GIS Cut Line= 5
 2172745.2549985374341.2325287182171951.95671941373981.756256256
2171775.85271151373981.7562562562171667.88418286373984.900970683
2170915.28450544374153.043701407
#Sta/Elev= 30
       0 1905.18    29.5 1902.96    72.8 1901.92   288.9 1902.65   479.8 1899.53
   543.9 1901.41   681.5 1898.74     765 1900.73   821.9 1899.69   924.8 1900.14
  1052.7 1898.93  1069.1 1898.63  1073.81897.487  1075.7 1896.41  1088.8  1895.8
  1098.61897.413  1105.2 1899.03  1118.4 1898.39  1131.5 1899.31  1208.2 1898.02
  1484.8 1897.92    1595 1896.53  1628.5 1897.39  1641.9 1895.96  1715.9 1896.23
  1809.1  1903.1  1844.8  1908.5  1883.3 1911.96  1900.8 1916.76  1926.2 1918.24
#Mann= 3 , 0 , 0
       0     .06       0  1073.8    .045       0  1098.6     .06       0
#XS Ineff= 2 , 0
          938.45 1900.85  1285.3         1900.88
Permanent Ineff=
       F       F
Bank Sta=1073.8,1098.6
XS Rating Curve= 0 ,0
Exp/Cntr(USF)=0,0
Exp/Cntr=0.3,0.1

Type RM Length L Ch R = 1 ,256     ,62.3,62.3,62.3
XS GIS Cut Line= 3
2172708.44513329374138.6945782592171810.44457021373877.980680171
2170776.10220038374022.939878202
#Sta/Elev= 30
       0 1901.76     346 1901.06   433.8 1898.97   444.1 1900.18   491.9 1900.98
   549.8 1900.34   662.7 1896.68     820 1898.85   943.9 1895.27  1012.2 1894.36
    1042 1896.33  1048.6 1894.77  1051.9 1892.86  1056.4 1892.39  1063.1 1892.66
  1068.5 1894.47  1071.8 1896.04  1081.7 1896.73  1092.1 1899.24  1115.4 1901.26
    1496 1900.35  1615.4 1896.34  1681.4 1896.89  1764.2 1900.86  1780.8 1899.66
    1794  1902.9  1860.3 1903.52  1890.1  1905.3  1931.9 1903.05  1979.5  1903.9
#Mann= 3 , 0 , 0
       0     .06       0  1048.6    .045       0  1068.5     .06       0
#XS Ineff= 2 , 0
          818.38 1898.89 1121.16         1901.23
Permanent Ineff=
       F       F
Bank Sta=1048.6,1068.5
XS Rating Curve= 0 ,0
Exp/Cntr(USF)=0,0
Exp/Cntr=0.3,0.1

Type RM Length L Ch R = 1 ,194     ,55.1,55.1,55.1
XS GIS Cut Line= 5
2172709.26437846374105.6527062922171792.10802639373835.833580706
2171789.91145976373835.3522499942171665.11554502373834.110105679
2170726.44697549 373930.65400331
#Sta/Elev= 30
       0 1902.09   288.1 1901.88   431.7 1899.42   438.5 1898.66   493.2 1898.91
   559.8 1896.87     654 1896.22   716.3 1897.64   773.7 1896.38   924.2  1895.4
   941.3 1894.26   951.5 1892.31  1007.5 1893.94  1056.5 1892.09  1069.9 1890.47
  1079.7 1892.16  1083.4 1893.06  1184.1 1896.12  1224.8 1899.71  1274.3 1901.46
  1524.9 1899.55  1643.7 1895.31  1665.1  1896.5  1676.7 1895.68  1689.8 1896.72
  1729.4 1896.47  1795.4 1898.45  1953.7 1895.72  1999.9 1897.75  2026.7  1897.5
#Mann= 4 ,-1 , 0
       0     .06       0  1056.5    .045       0  1079.7     .06       0
  1083.4     .06       0
#XS Ineff= 2 , 0
          962.69 1895.37 1274.56         1901.52
Permanent Ineff=
       F       F
Bank Sta=1056.5,1079.7
XS Rating Curve= 0 ,0
Exp/Cntr=0.3,0.1

Type RM Length L Ch R = 1 ,139     ,19.2,19.2,19.2
XS GIS Cut Line= 4
2172710.08362363374072.6108343252171771.65975894373793.073390647
 2171641.6782293373773.156865943 2170676.7917506373838.368128418
#Sta/Elev= 30
       0 1902.85   247.6 1902.41   367.9 1897.27   559.6 1895.83   627.8 1897.26
   709.6  1893.4   799.3 1895.09   874.6 1890.52   960.1 1889.75    1062 1891.05
    1067 1889.81  1076.4 1890.92  1076.9 1891.01  1129.8 1890.52  1205.5 1892.67
  1411.2 1894.22    1442 1895.98  1468.5 1900.41  1524.4 1901.47  1613.2 1896.18
  1662.6 1894.84    1679 1896.22    1748 1896.58  1787.5 1899.71  1826.9 1899.47
  1902.6 1894.45  1988.1 1894.24  2050.6 1891.45  2063.7 1897.81  2077.8 1898.72
#Mann= 4 ,-1 , 0
       0     .06       0    1062    .045       0  1076.4     .06       0
  1076.9     .06       0
Bank Sta=1062,1076.4
XS Rating Curve= 0 ,0
Exp/Cntr(USF)=0,0
Exp/Cntr=0.3,0.1

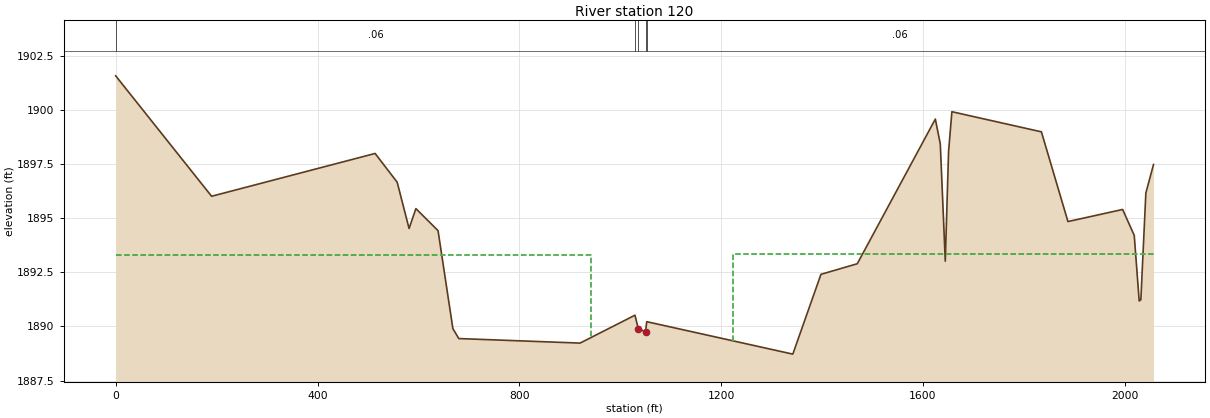
Type RM Length L Ch R = 1 ,120     ,120,120,120
XS GIS Cut Line= 6
2172696.42976926  373997.71436812171767.56673326373773.888552615
2171754.58129988373771.0428273792171625.68945212 373752.04195895
 2171604.2840508373751.2801133462170668.95970135373798.132352229
#Sta/Elev= 30
       0 1901.59   190.1 1896.02   514.2    1898   557.9 1896.67   581.5 1894.53
     595 1895.45   638.9 1894.43   668.3  1889.9     680 1889.44   920.4 1889.23
  1029.2 1890.52  1035.9 1889.88  1050.21889.766  1052.5 1890.22    1342 1888.72
  1397.8 1892.41  1469.8  1892.9  1624.5 1899.59  1634.3 1898.44  1644.2 1893.02
  1650.7 1898.08  1657.3 1899.93  1834.7    1899  1887.3 1894.85  1995.7 1895.41
  2018.7 1894.21  2028.5 1891.18  2031.8 1891.23  2041.7 1896.17  2056.9 1897.49
#Mann= 5 ,-1 , 0
       0     .06       0  1029.2     .06       0  1035.9    .045       0
  1050.2     .06       0  1052.5     .06       0
#XS Ineff= 2 , 0
          942.19  1893.3 1223.72         1893.35
Permanent Ineff=
       F       F
Bank Sta=1035.9,1050.2
XS Rating Curve= 0 ,0
Exp/Cntr=0.3,0.1
LCMann Table=0

Chan Stop Cuts=-1
Use User Specified Reach Order=0
Composite Channel Slope=5